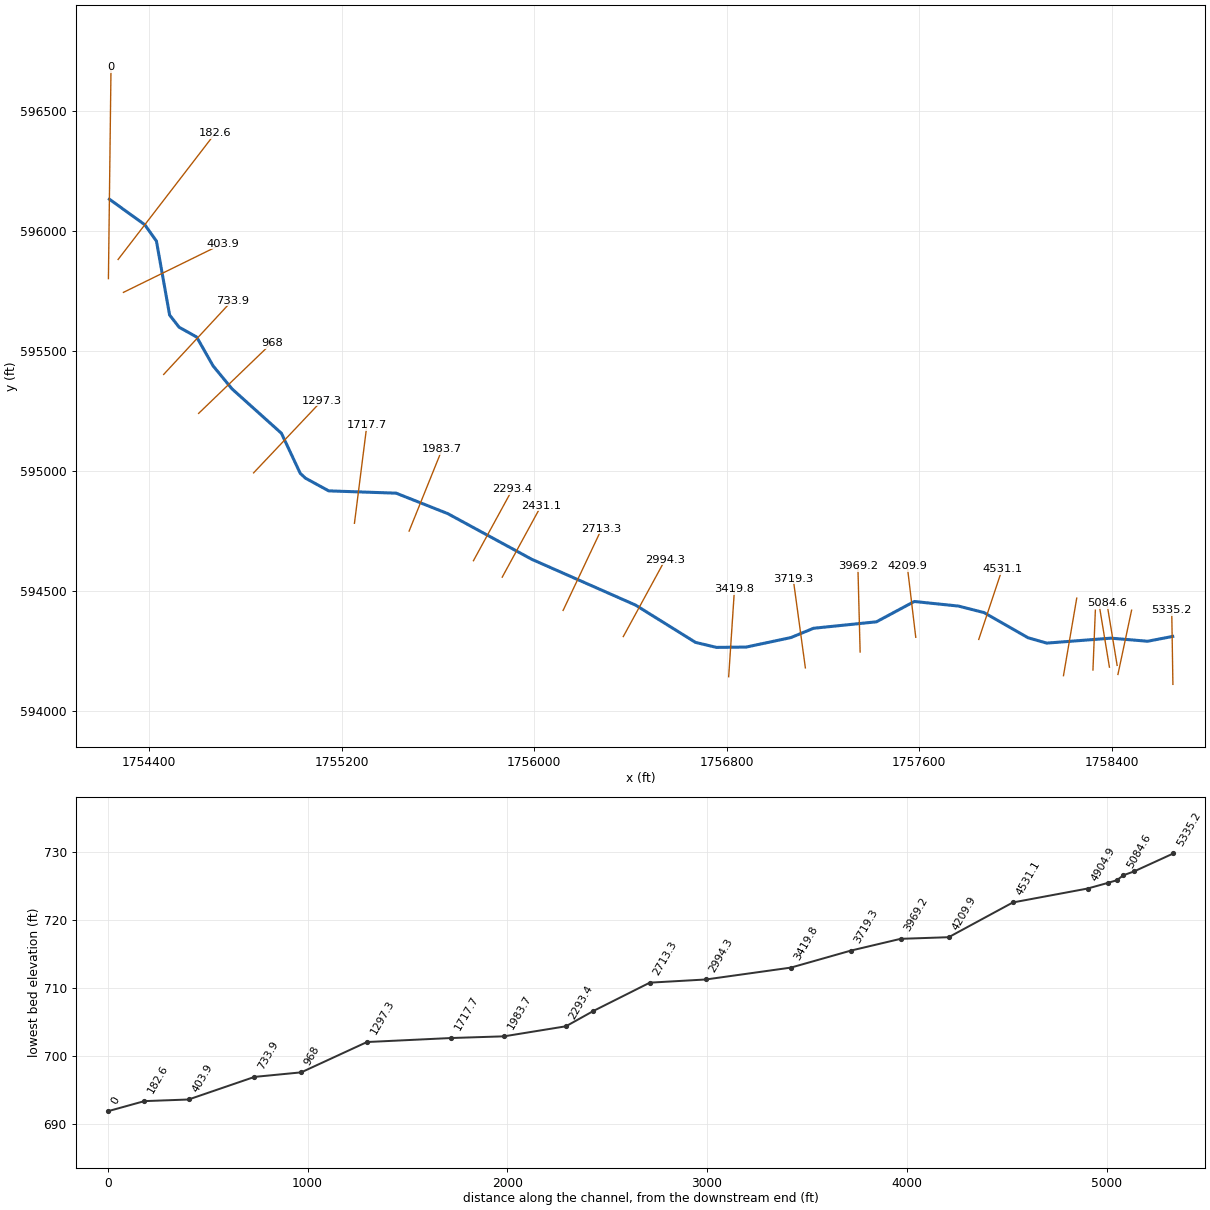
--- RFkClenden.prj (project) ---

Proj Title=RFkClenden
Current Plan=p01
Default Exp/Contr=0,0
English Units
Geom File=g01
Flow File=f01
Plan File=p01
BEGIN DESCRIPTION:
AMEC Environment & Infrastructure, 2013
Projection: NAD 1983 State Plane West Virginia South FIPS 4702 (US Feet)
Vertical Datum: NAVD 1988
END DESCRIPTION:
DSS Export Rating Curves= 0
DSS Export Rating Curve Sorted= 0
DSS Export Volume Flow Curves= 0
DXF OffsetX= 0
DXF OffsetY= 0
DXF ScaleX= 0
DXF ScaleY= 0

--- RFkClenden.p01 (plan) ---

Plan Title=Floodplain
Program Version=4.00
Geom File=g01
Flow File=f01
K Sum by GR=0
Std Step Tol=0.01
Critical Tol=0.01
Num of Std Step Trials=20
Max Error Tol=0.3
Flow Tol Ratio=0.001
Split Flow NTrial=30
Split Flow Tol=0.02
Split Flow Ratio=0.02
Log Output Level=0
Friction Slope Method=1
Unsteady Friction Slope Method=2
Unsteady Bridges Friction Slope Method=1
Global Log Level=0
CheckData=False
Run HTab=0
Run UNet=0
Run PostProcess=0
UNET Theta=0
UNET Theta Warmup=0
UNET ZTol=0
UNET ZSATol=0
UNET MxIter=0
UNET MaxInSteps=0
UNET DtIC=0
UNET DtMin=0
UNET MaxCRTS=0
UNET WFStab=0
UNET SFStab=0
UNET WFX=0
UNET SFX=0
UNET DSS MLevel=0
UNET DZMax Abort=0
UNET Convert EG Bridges=0
UNET Use Existing IB Tables=0
UNET Froude Limit=0
UNET Froude Power=0
Write IC File=0
Echo Input=False
Echo Output=False
Write Detailed=0

--- RFkClenden.f01 (steady flow) ---

Flow Title=USGS Regress. Eqn. (2010) - Western-Plateaus
Program Version=4.10
Number of Profiles= 1
Profile Names=P100yr
River Rch & RM=RFkClenden,Main            ,5335.2
     855
River Rch & RM=RFkClenden,Main            ,5084.6
     856
River Rch & RM=RFkClenden,Main            ,4531.1
     942
River Rch & RM=RFkClenden,Main            ,4209.9
     945
River Rch & RM=RFkClenden,Main            ,3969.2
     973
River Rch & RM=RFkClenden,Main            ,2994.3
     994
River Rch & RM=RFkClenden,Main            ,2431.1
    1036
River Rch & RM=RFkClenden,Main            ,1717.7
    1058
River Rch & RM=RFkClenden,Main            ,182.6
    1114
River Rch & RM=RFkClenden,Main            ,0
    1115
Boundary for River Rch & Prof#=RFkClenden,Main            , 1
Up Type= 0
Dn Type= 1
Dn Known WS=698.56
DSS Import GetInterval= 0
DSS Import GetPeak= 0
DSS Import FillOption= 0

--- RFkClenden.g01 (geometry) ---

Geom Title=USGS 3m DEM
Program Version=4.10

River Reach=RFkClenden      ,Main
Reach XY= 30
     1758653.823      594310.961     1758549.656      594290.823
     1758396.878       594303.67     1758130.096      594283.068
     1758052.665       594305.29     1757869.679      594410.151
     1757763.689      594437.292     1757579.688      594456.433
     1757422.367      594371.769     1757161.169      594344.946
     1757066.551      594306.057     1756880.787       594266.56
     1756757.089      594265.258     1756670.284      594286.092
     1756420.978      594441.474     1755990.314      594631.877
     1755640.542      594822.382     1755425.901      594907.684
     1755145.519      594917.233     1755048.842      594970.145
     1755027.117      594990.497     1754948.992      595157.163
     1754743.754      595341.961     1754665.195      595437.448
     1754596.619      595558.107     1754523.702      595598.906
     1754484.206      595649.687     1754429.399      595957.738
     1754381.135      596025.794     1754233.904      596132.213

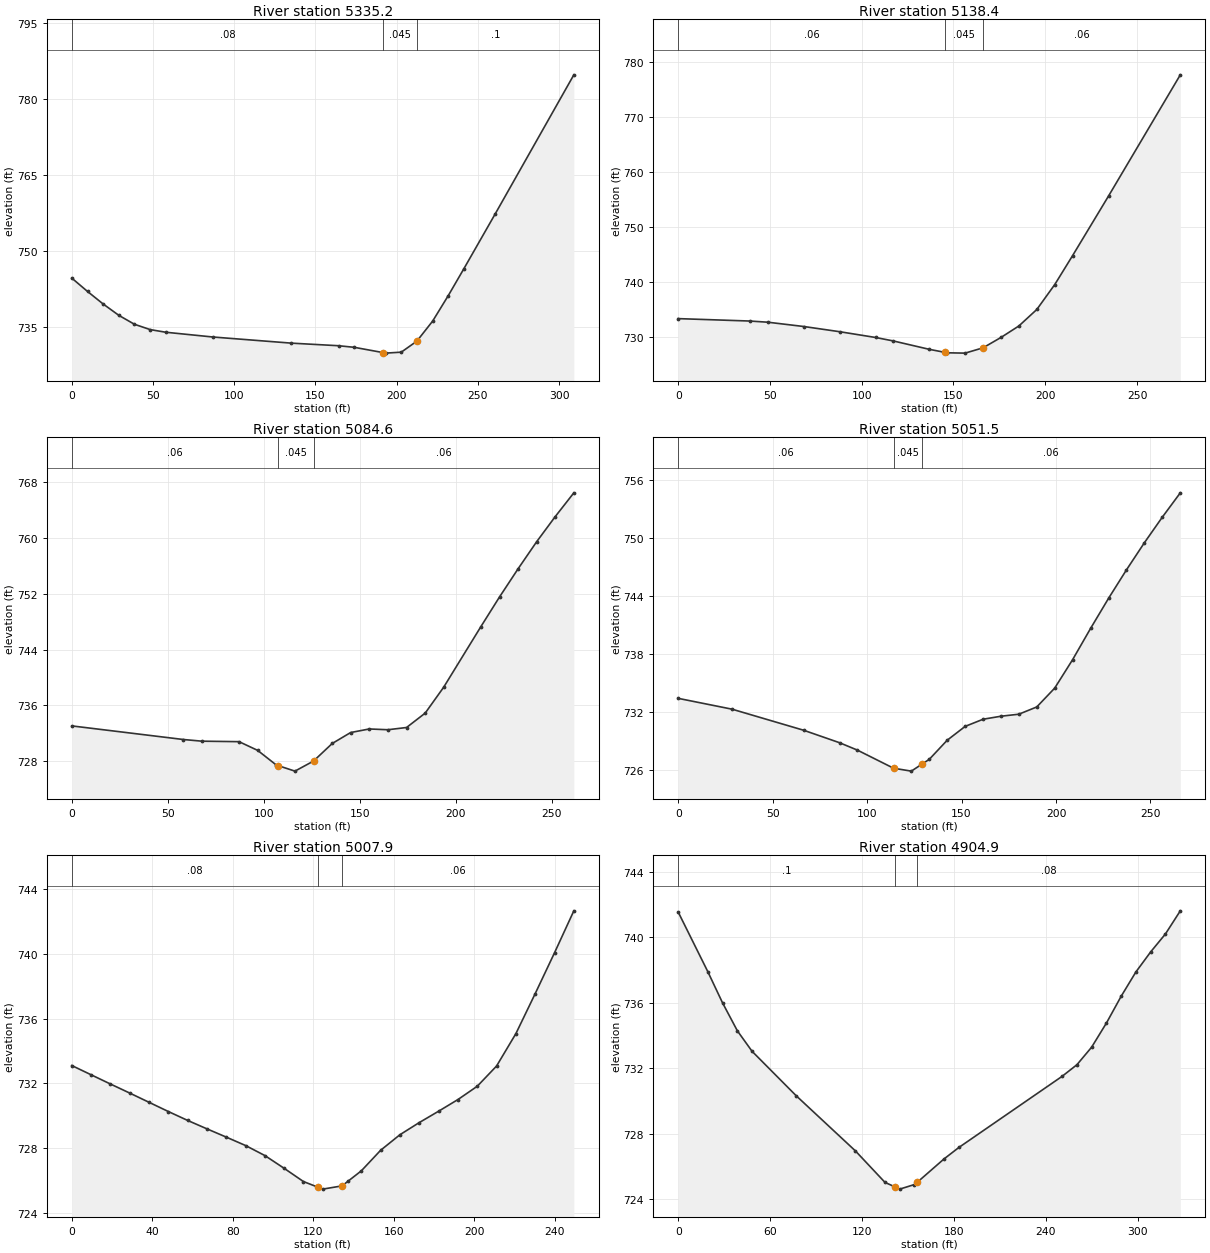
Type RM Length L Ch R = 1 ,5335.2  ,201.7,196.8,191.9
XS GIS Cut Line= 2
     1758654.709      594111.264     1758649.792      594420.214
#Sta/Elev= 20
       0  744.62     9.7  741.98    19.3  739.51      29  737.26    38.6   735.5
    48.3  734.45    57.9  733.93    86.9  732.99   135.2  731.78   164.2  731.27
   173.8  730.96   191.5  729.92   193.1  729.81   202.8     730   212.4  732.18
   222.1  736.13   231.7  741.15   241.4  746.51   260.7  757.34     309  784.73
#Mann= 3 , 0 , 0
       0     .08       0   191.5    .045       0   212.4      .1       0
Bank Sta=191.5,212.4
XS Rating Curve= 0 ,0
Exp/Cntr=0.3,0.1

Type RM Length L Ch R = 1 ,5138.4  ,45.2,53.7,62
XS GIS Cut Line= 2
     1758426.185      594152.584     1758482.923      594420.201
#Sta/Elev= 19
       0  733.42    39.1  732.98    48.8  732.77    68.4  731.99    87.9  731.05
   107.5     730   117.2  729.37   136.8  727.85   145.3   727.3   146.6  727.22
   156.3  727.16   166.1  728.12   175.9  730.01   185.6  732.08   195.4  735.08
   205.2  739.61   214.9  744.85   234.5  755.67   273.6  777.65
#Mann= 3 , 0 , 0
       0     .06       0   145.3    .045       0   166.1     .06       0
Bank Sta=145.3,166.1
XS Rating Curve= 0 ,0
Exp/Cntr=0.3,0.1

Type RM Length L Ch R = 1 ,5084.6  ,33.2,33.1,33.2
XS GIS Cut Line= 2
     1758422.844      594190.376      1758380.51      594448.341
#Sta/Elev= 22
       0  733.07    58.1  731.12    67.8  730.88    87.1  730.81    96.8  729.56
   106.5  727.46   107.3  727.39   116.2  726.59   125.9  728.04   135.6  730.55
   145.2  732.12   154.9  732.63   164.6  732.52   174.3  732.84     184   734.9
   193.6   738.6     213  747.29   222.7  751.54   232.4  755.59     242  759.44
   251.7  763.05   261.4  766.46
#Mann= 3 , 0 , 0
       0     .06       0   107.3    .045       0   125.9     .06       0
Bank Sta=107.3,125.9
XS Rating Curve= 0 ,0
Exp/Cntr=0.3,0.1

Type RM Length L Ch R = 1 ,5051.5  ,48.4,43.7,39.2
XS GIS Cut Line= 2
     1758390.839      594182.751       1758347.8      594445.005
#Sta/Elev= 23
       0  733.39    28.5  732.27    66.4  730.09    85.4   728.8    94.9  728.03
     114  726.16   123.4  725.86     129  726.58   132.9  727.08   142.4  729.06
   151.9  730.49   161.4  731.23   170.8  731.54   180.3  731.75   189.8   732.5
   199.3  734.45   208.8   737.4   218.3  740.63   227.8  743.74   237.3  746.69
   246.8   749.5   256.3  752.15   265.8  754.66
#Mann= 3 , 0 , 0
       0     .06       0     114    .045       0     129     .06       0
Bank Sta=114,129
XS Rating Curve= 0 ,0
Exp/Cntr=0.3,0.1

Type RM Length L Ch R = 1 ,5007.9  ,106.3,103,100.2
XS GIS Cut Line= 2
     1758322.348      594170.914     1758332.327      594420.189
#Sta/Elev= 29
       0   733.1     9.6  732.53    19.2  731.96    28.8   731.4    38.4  730.83
      48  730.26    57.6  729.71    67.2  729.19    76.8  728.68    86.4  728.16
      96  727.54   105.6  726.75   115.1  725.94   122.3  725.59   124.7  725.47
   134.3  725.67   137.3  725.96   143.9   726.6   153.5  727.87   163.1  728.83
   172.7  729.58   182.3  730.28   191.9     731   201.5  731.82   211.1  733.07
   220.7  735.07   230.3  737.54   239.9  740.06   249.5  742.65
#Mann= 3 , 0 , 0
       0     .08       0   122.3    .045       0   134.3     .06       0
Bank Sta=122.3,134.3
XS Rating Curve= 0 ,0
Exp/Cntr=0.3,0.1

Type RM Length L Ch R = 1 ,4904.9  ,376.7,373.8,369.8
XS GIS Cut Line= 2
      1758199.76      594147.327     1758254.949      594470.393
#Sta/Elev= 23
       0  741.53    19.3   737.9    28.9     736    38.6  734.29    48.2  733.04
    77.1  730.32   115.7  726.96     135  725.04   141.2  724.78   144.6  724.63
   154.2  724.91   156.2  725.06   173.5  726.47   183.2  727.17   250.6  731.51
   260.3  732.22   269.9  733.29   279.6  734.77   289.2   736.4   298.8  737.88
   308.5  739.11   318.1   740.2   327.8  741.61
#Mann= 3 , 0 , 0
       0      .1       0   141.2    .045       0   156.2     .08       0
Bank Sta=141.2,156.2
XS Rating Curve= 0 ,0
Exp/Cntr=0.3,0.1

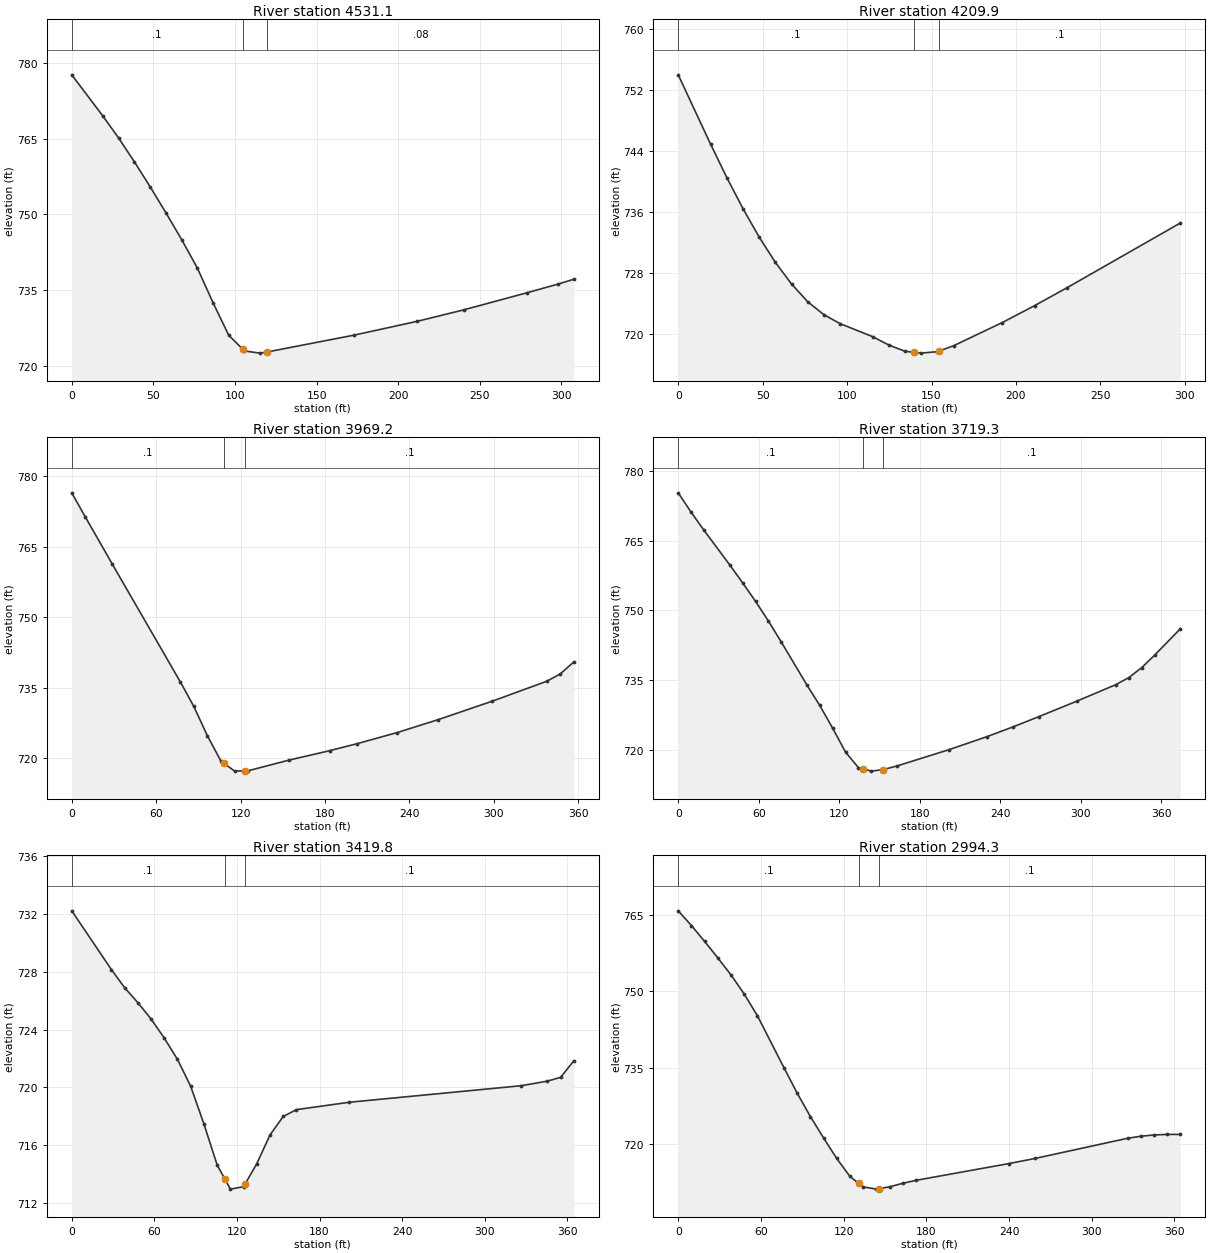
Type RM Length L Ch R = 1 ,4531.1  ,311.3,321.2,331.1
XS GIS Cut Line= 2
     1757847.603      594298.462     1757944.693      594590.366
#Sta/Elev= 20
       0  777.61    19.2   769.4    28.8  765.08    38.4  760.39    48.1  755.43
    57.7  750.32    67.3  745.04    76.9  739.43    86.5  732.59    96.1  726.15
   104.7  723.36   105.8     723   115.4  722.58   119.7  722.81     173  726.14
   211.5  728.86   240.3  731.15   278.8  734.51     298  736.24   307.6  737.19
#Mann= 3 , 0 , 0
       0      .1       0   104.7    .045       0   119.7     .08       0
Bank Sta=104.7,119.7
XS Rating Curve= 0 ,0
Exp/Cntr=0.3,0.1

Type RM Length L Ch R = 1 ,4209.9  ,242.7,240.7,238.6
XS GIS Cut Line= 2
      1757585.78      594307.248     1757550.682      594602.444
#Sta/Elev= 22
       0  753.93    19.2  744.82    28.8  740.45    38.4  736.37      48  732.64
    57.5  729.36    67.1  726.52    76.7  724.19    86.3  722.49    95.9  721.32
   115.1  719.62   124.7  718.52   134.2  717.71   139.6  717.57   143.8  717.46
   153.4  717.65   154.6  717.75     163  718.42   191.8  721.46     211  723.68
   230.2  726.03   297.3  734.51
#Mann= 3 , 0 , 0
       0      .1       0   139.6    .045       0   154.6      .1       0
Bank Sta=139.6,154.6
XS Rating Curve= 0 ,0
Exp/Cntr=0.3,0.1

Type RM Length L Ch R = 1 ,3969.2  ,247.7,249.8,252.5
XS GIS Cut Line= 2
     1757354.559      594245.897     1757345.197      594602.724
#Sta/Elev= 20
       0  776.47     9.6  771.35    28.9  761.25    77.2  736.22    86.8  730.98
    96.5  724.71   106.1  719.34   108.3  718.86   115.8  717.22   123.3  717.28
   125.4   717.3   154.4  719.56   183.3  721.57   202.6  723.04   231.5  725.44
   260.5  728.18   299.1  732.12   337.7  736.35   347.3   737.9     357  740.48
#Mann= 3 , 0 , 0
       0      .1       0   108.3    .045       0   123.3      .1       0
Bank Sta=108.3,123.3
XS Rating Curve= 0 ,0
Exp/Cntr=0.3,0.1

Type RM Length L Ch R = 1 ,3719.3  ,303.6,299.5,294.7
XS GIS Cut Line= 2
     1757126.921      594179.965      1757076.32      594550.693
#Sta/Elev= 27
       0  775.27     9.6  771.11    19.2  767.23    38.4  759.78      48  755.93
    57.6  751.96    67.2  747.73    76.8  743.22    95.9  733.99   105.5  729.58
   115.1   724.7   124.7  719.57   134.3  716.23   137.9  715.95   143.9  715.48
   152.9  715.81   163.1   716.6   201.5  720.06   230.3  722.91   249.4  724.97
   268.6  727.17   297.4  730.55   326.2  734.07   335.8  735.57   345.4  737.71
     355  740.38   374.2  746.06
#Mann= 3 , 0 , 0
       0      .1       0   137.9    .045       0   152.9      .1       0
Bank Sta=137.9,152.9
XS Rating Curve= 0 ,0
Exp/Cntr=0.3,0.1

Type RM Length L Ch R = 1 ,3419.8  ,435.3,425.5,415.7
XS GIS Cut Line= 2
     1756808.112      594143.143     1756832.195      594507.064
#Sta/Elev= 23
       0   732.2    28.8  728.14    38.4  726.89      48  725.86    57.6  724.73
    67.2  723.41    76.8  721.94    86.4  720.08      96  717.48   105.6  714.65
     111  713.71   115.2  712.98   124.8  713.15     126  713.35   134.4  714.74
     144  716.72   153.6     718   163.2  718.47   201.6  718.98   326.3  720.12
   345.5  720.44   355.1   720.7   364.7  721.85
#Mann= 3 , 0 , 0
       0      .1       0     111    .045       0     126      .1       0
Bank Sta=111,126
XS Rating Curve= 0 ,0
Exp/Cntr=0.3,0.1

Type RM Length L Ch R = 1 ,2994.3  ,279.6,281.1,282.2
XS GIS Cut Line= 2
     1756370.019      594310.248      1756544.08      594630.276
#Sta/Elev= 27
       0  765.81     9.6  762.92    19.2   759.8    28.8  756.55    38.4   753.2
    47.9  749.48    57.5  745.21    76.7  735.05    86.3  730.06    95.9  725.45
   105.5  721.25     115  717.24   124.6  713.72   130.9  712.37   134.2  711.67
   143.8  711.23   145.9  711.33   153.4  711.69     163  712.38   172.6  712.96
   239.7  716.23   258.8  717.24     326   721.2   335.5   721.6   345.1  721.85
   354.7  721.96   364.3  721.96
#Mann= 3 , 0 , 0
       0      .1       0   130.9    .045       0   145.9      .1       0
Bank Sta=130.9,145.9
XS Rating Curve= 0 ,0
Exp/Cntr=0.3,0.1

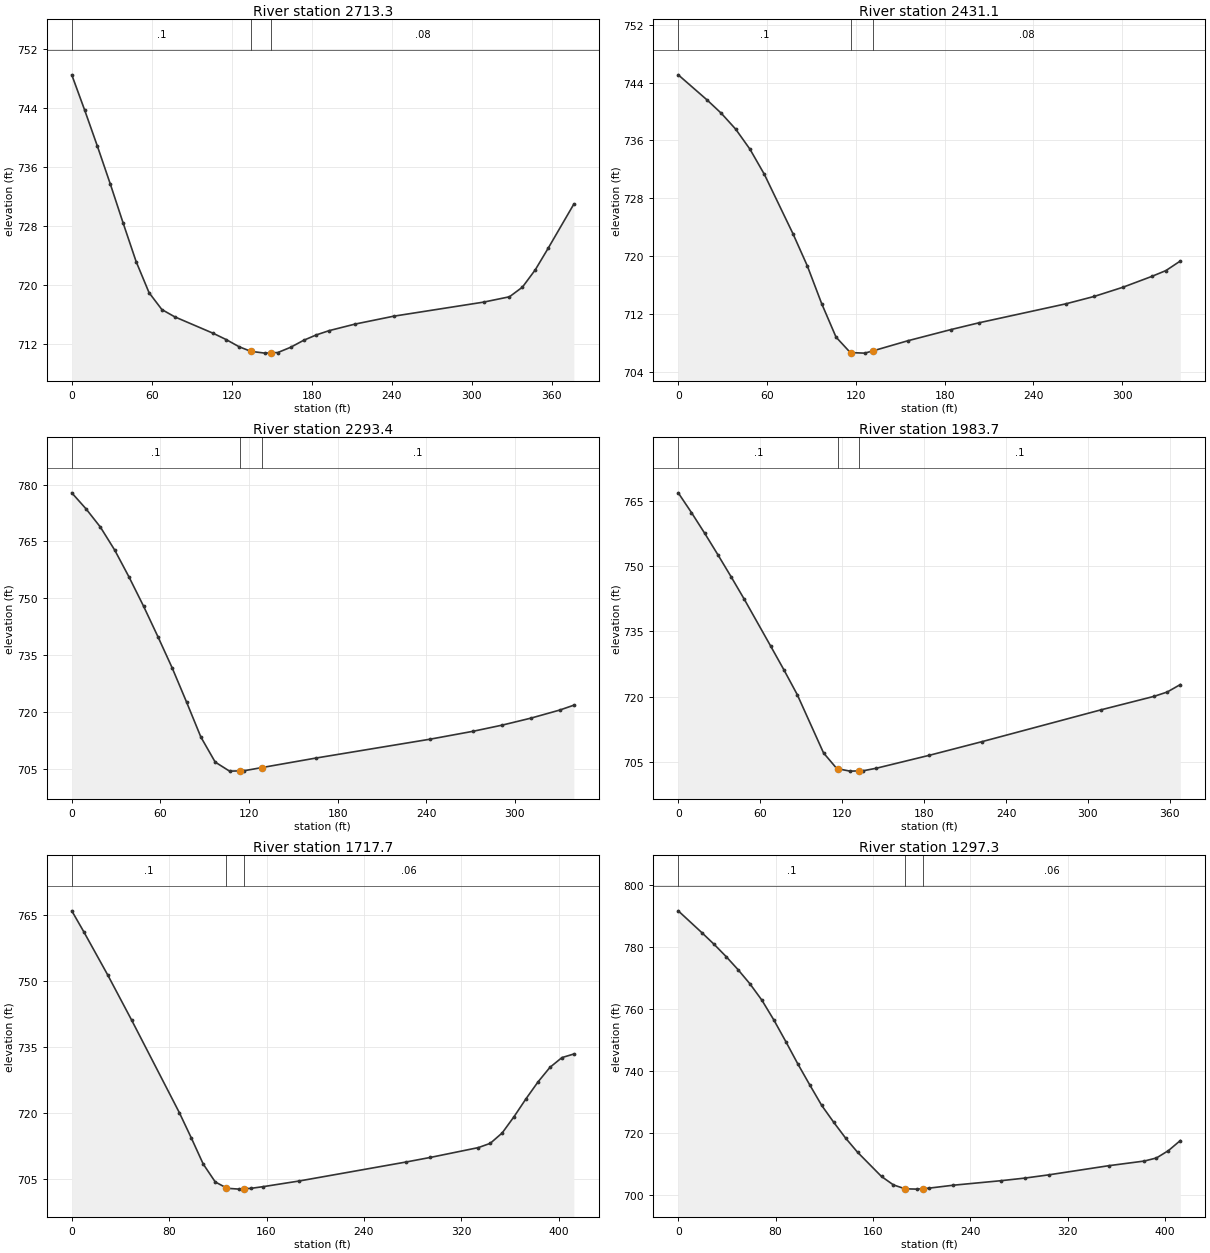
Type RM Length L Ch R = 1 ,2713.3  ,283.5,282.2,280.9
XS GIS Cut Line= 2
     1756119.805      594419.161     1756280.475      594759.922
#Sta/Elev= 28
       0  748.44     9.7  743.65    19.3  738.74      29  733.61    38.6  728.34
    48.3  723.15      58  718.94    67.6  716.66    77.3  715.67   106.3  713.43
   115.9  712.59   125.6  711.62   134.4     711   144.9  710.76   149.4   710.8
   154.6  710.84   164.2  711.55   173.9  712.49   183.5  713.23   193.2  713.81
   212.5  714.69   241.5  715.76   309.1  717.67   328.4  718.39   338.1  719.69
   347.8  722.05   357.4  724.95   376.7  730.94
#Mann= 3 , 0 , 0
       0      .1       0   134.4    .045       0   149.4     .08       0
Bank Sta=134.4,149.4
XS Rating Curve= 0 ,0
Exp/Cntr=0.3,0.1

Type RM Length L Ch R = 1 ,2431.1  ,137.7,137.7,137.7
XS GIS Cut Line= 2
     1755866.765      594557.703      1756028.79       594855.69
#Sta/Elev= 23
       0  745.08    19.4  741.62    29.1  739.76    38.8  737.57    48.5  734.78
    58.2  731.31    77.5  723.11    87.2  718.66    96.9  713.44   106.6  708.81
   116.3  706.66   116.7  706.66     126  706.59   131.7  706.91   155.1   708.3
   184.1  709.84   203.5   710.8   261.7   713.4     281  714.43   300.4   715.7
   319.8  717.19   329.5  718.01   339.2  719.33
#Mann= 3 , 0 , 0
       0      .1       0   116.7    .045       0   131.7     .08       0
Bank Sta=116.7,131.7
XS Rating Curve= 0 ,0
Exp/Cntr=0.3,0.1

Type RM Length L Ch R = 1 ,2293.4  ,307.1,309.8,312.4
XS GIS Cut Line= 2
     1755747.223      594626.316     1755909.804      594924.818
#Sta/Elev= 22
       0  777.82     9.7  773.57    19.4  768.76    29.1  762.68    38.8  755.56
    48.6  747.89    58.3  739.85      68  731.57    77.7  722.58    87.4  713.33
    97.1  706.72   106.8  704.33   113.7  704.39   116.5  704.42   128.7  705.27
   165.1  707.77   242.8  712.78   271.9  714.87   291.4  716.48   310.8  718.32
   330.2  720.44   339.9  721.74
#Mann= 3 , 0 , 0
       0      .1       0   113.7    .045       0   128.7      .1       0
Bank Sta=113.7,128.7
XS Rating Curve= 0 ,0
Exp/Cntr=0.3,0.1

Type RM Length L Ch R = 1 ,1983.7  ,260.1,265.9,271.8
XS GIS Cut Line= 2
     1755479.764      594749.791     1755617.108      595090.828
#Sta/Elev= 22
       0  766.89     9.7  762.34    19.4  757.57      29  752.66    38.7  747.58
    48.4  742.38    67.7  731.61    77.4  726.14    87.1  720.48   106.4  707.03
   116.1  703.44   117.2  703.37   125.8  702.85   132.2   702.9   135.4  702.93
   145.1  703.52   183.8  706.49   222.5  709.64   309.6  716.96   348.3  720.05
     358  721.05   367.6  722.77
#Mann= 3 , 0 , 0
       0      .1       0   117.2    .045       0   132.2      .1       0
Bank Sta=117.2,132.2
XS Rating Curve= 0 ,0
Exp/Cntr=0.3,0.1

Type RM Length L Ch R = 1 ,1717.7  ,433.3,420.4,406.4
XS GIS Cut Line= 2
     1755252.544      594782.285     1755304.227      595191.559
#Sta/Elev= 26
       0  765.95     9.8  761.22    29.5  751.37    49.1  741.12    88.4     720
    98.2  714.26     108  708.31   117.9  704.23   126.6  702.95   127.7  702.79
   137.5   702.6   141.6  702.68   147.3  702.78   157.2  703.16   186.6  704.44
     275  708.79   294.7  709.82     334  712.05   343.8  713.02   353.6  715.38
   363.4  719.11   373.2  723.17   383.1  727.02   392.9  730.33   402.7  732.54
   412.5  733.36
#Mann= 3 , 0 , 0
       0      .1       0   126.6    .045       0   141.6     .06       0
Bank Sta=126.6,141.6
XS Rating Curve= 0 ,0
Exp/Cntr=0.3,0.1

Type RM Length L Ch R = 1 ,1297.3  ,331.7,329.3,328
XS GIS Cut Line= 2
     1754833.316      594992.226     1755116.378      595292.296
#Sta/Elev= 30
       0  791.75    19.6  784.64    29.5  780.94    39.3  777.02    49.1   772.8
    58.9  768.22    68.8   762.9    78.6  756.52    88.4  749.58    98.2  742.43
     108  735.66   117.9  728.99   127.7  723.59   137.5  718.47   147.3  713.92
     167  706.09   176.8  703.37   186.4  702.11   196.4  702.01   201.4  702.18
   206.3  702.34   225.9  703.27   265.2  704.73   284.8  705.57   304.5  706.62
   353.6  709.56     383  711.07   392.9  712.06   402.7  714.42   412.5  717.67
#Mann= 3 , 0 , 0
       0      .1       0   186.4    .045       0   201.4     .06       0
Bank Sta=186.4,201.4
XS Rating Curve= 0 ,0
Exp/Cntr=0.3,0.1

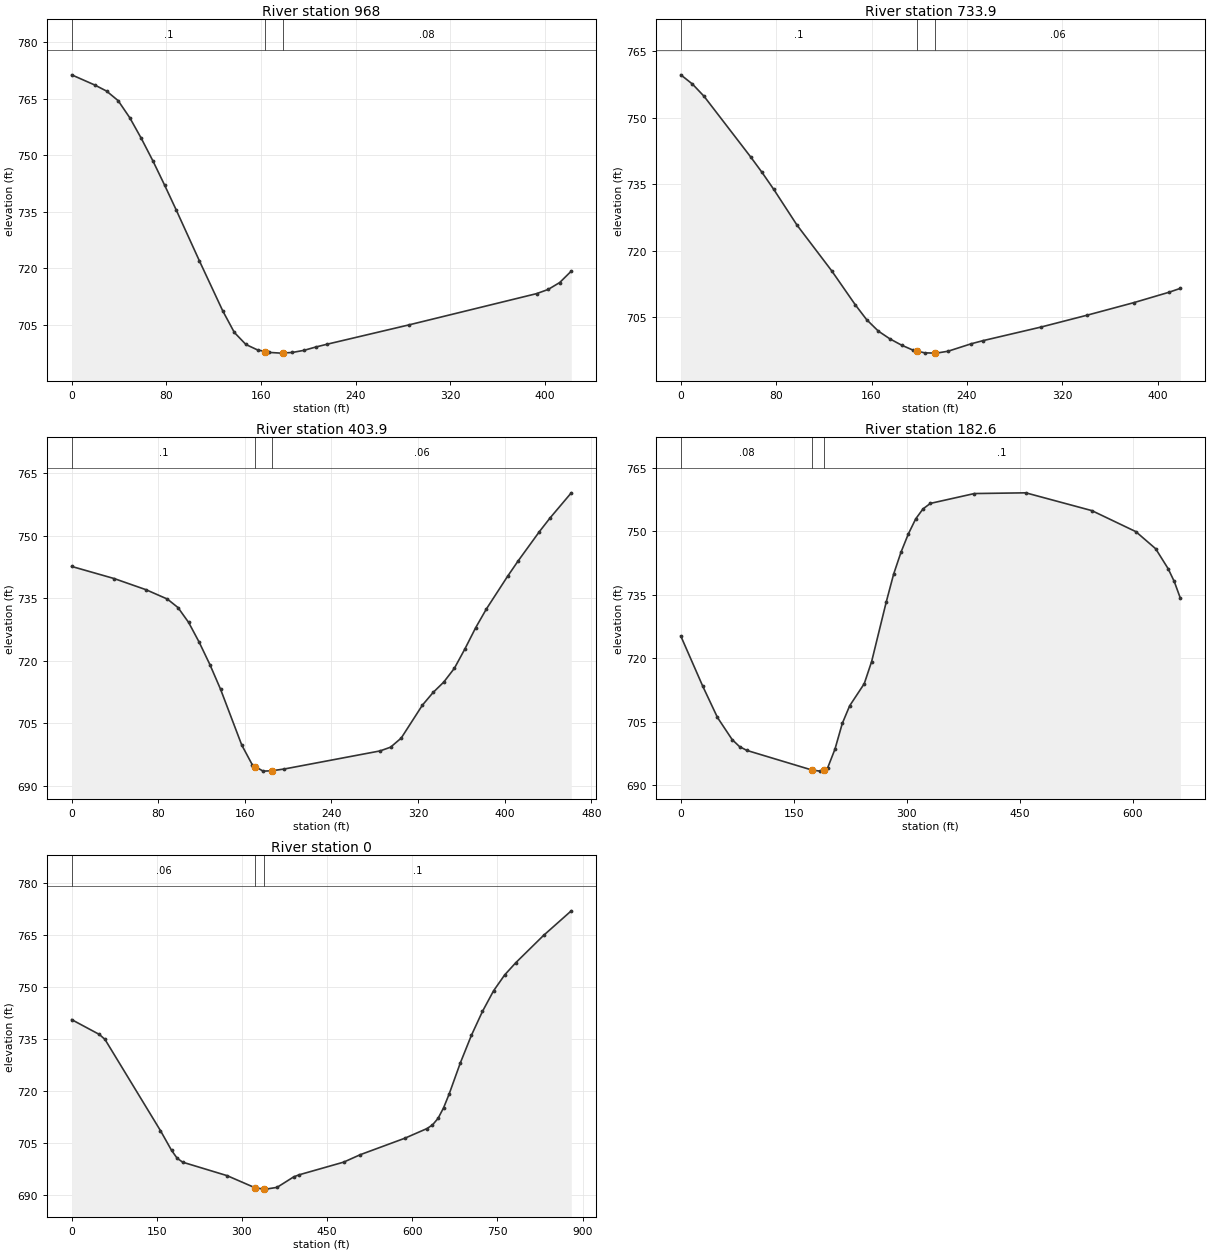
Type RM Length L Ch R = 1 ,968     ,232.5,234.1,235.7
XS GIS Cut Line= 2
     1754604.815       595240.02     1754908.788      595533.208
#Sta/Elev= 27
       0  771.39    19.6  768.68    29.5  767.08    39.3  764.54    49.1  760.02
    58.9  754.51    68.8  748.48    78.6   742.1    88.4  735.52     108  722.01
   127.7  708.76   137.5  703.03   147.3  699.83   157.1  698.39   163.7  697.95
     167  697.73   176.8  697.54   178.7  697.57   186.6  697.72   196.4  698.28
   206.2  699.15   216.1  699.92   284.8  705.01   392.9  713.32   402.7  714.43
   412.5  716.27   422.3   719.3
#Mann= 3 , 0 , 0
       0      .1       0   163.7    .045       0   178.7     .08       0
Bank Sta=163.7,178.7
XS Rating Curve= 0 ,0
Exp/Cntr=0.3,0.1

Type RM Length L Ch R = 1 ,733.9   ,338.6,330,322.1
XS GIS Cut Line= 2
      1754459.53      595402.271     1754744.152      595709.847
#Sta/Elev= 26
       0  759.67     9.8  757.58    19.5  754.83    58.5  741.18    68.2  737.63
      78  733.81    97.5  725.75   126.7   715.4   146.2  707.84   155.9  704.42
   165.7  701.84   175.4  700.09   185.2  698.67   194.9  697.53   198.1  697.33
   204.7  696.93   213.1  696.88   214.4  696.87   224.2   697.3   243.6  698.98
   253.4  699.68   302.1  702.75   341.1  705.45   380.1  708.27   409.3  710.59
   419.1  711.49
#Mann= 3 , 0 , 0
       0      .1       0   198.1    .045       0   213.1     .06       0
Bank Sta=198.1,213.1
XS Rating Curve= 0 ,0
Exp/Cntr=0.3,0.1

Type RM Length L Ch R = 1 ,403.9   ,210.5,221.3,231
XS GIS Cut Line= 2
     1754292.181      595744.041     1754706.361      595947.658
#Sta/Elev= 30
       0   742.6    39.3  739.69    68.7  737.02    88.4  734.78    98.2  732.75
     108   729.2   117.8  724.44   127.7  719.07   137.5  713.19   157.1   699.8
   166.9  695.04   169.7  694.62   176.8  693.54   184.7  693.62   196.4  694.05
   284.8  698.38   294.6  699.28   304.4  701.46     324  709.36   333.9   712.4
   343.7  714.88   353.5  718.18   363.3  722.86   373.2  727.92     383  732.37
   402.6  740.21   412.4  743.92   432.1  750.96   441.9  754.22   461.5  760.24
#Mann= 3 , 0 , 0
       0      .1       0   169.7    .045       0   184.7     .06       0
Bank Sta=169.7,184.7
XS Rating Curve= 0 ,0
Exp/Cntr=0.3,0.1

Type RM Length L Ch R = 1 ,182.6   ,167.2,182.6,198
XS GIS Cut Line= 3
      1754270.17      595881.234     1754644.032      596368.286
     1754674.145      596407.516
#Sta/Elev= 30
       0  725.26    29.2  713.37    48.7  705.99    68.2  700.76      78   699.1
    87.7   698.2   174.7  693.53   185.2   693.3   189.7  693.64   194.9  694.03
   204.7   698.5   214.4  704.57   224.2  708.75   243.6  713.99   253.4  719.23
   272.9  733.39   282.6   739.9   292.4   745.1   302.1  749.39   311.9  752.97
   321.6  755.33   331.4  756.63   389.8  758.96   458.1  759.13   545.8  754.92
   604.2  749.95   630.5  745.91     647  741.21   655.2  738.16   663.4  734.15
#Mann= 3 , 0 , 0
       0     .08       0   174.7    .045       0   189.7      .1       0
Bank Sta=174.7,189.7
XS Rating Curve= 0 ,0
Exp/Cntr=0.3,0.1

Type RM Length L Ch R = 1 ,0       ,12.2,0,0
XS GIS Cut Line= 2
     1754229.846      595801.364     1754240.638      596681.408
#Sta/Elev= 30
       0  740.71    48.9  736.42    58.7     735   156.5  708.67     176  702.99
   185.8  700.73   195.6  699.58   273.8   695.7   323.4  692.18   338.4  691.83
   342.3  691.81   361.8  692.32   391.2  695.35   400.9  695.95   479.2   699.6
   508.5  701.75   586.7  706.48   625.9  709.28   635.6  710.33   645.4  712.22
   655.2  715.28     665  719.26   684.5  728.15   704.1  736.15   723.6  743.06
   743.2  749.02   762.8  753.61   782.3  757.12   831.2  764.99   880.1  772.09
#Mann= 3 , 0 , 0
       0     .06       0   323.4    .045       0   338.4      .1       0
Bank Sta=323.4,338.4
XS Rating Curve= 0 ,0
Exp/Cntr=0.3,0.1

Chan Stop Cuts=-1
Use User Specified Reach Order=0
Composite Channel Slope=5